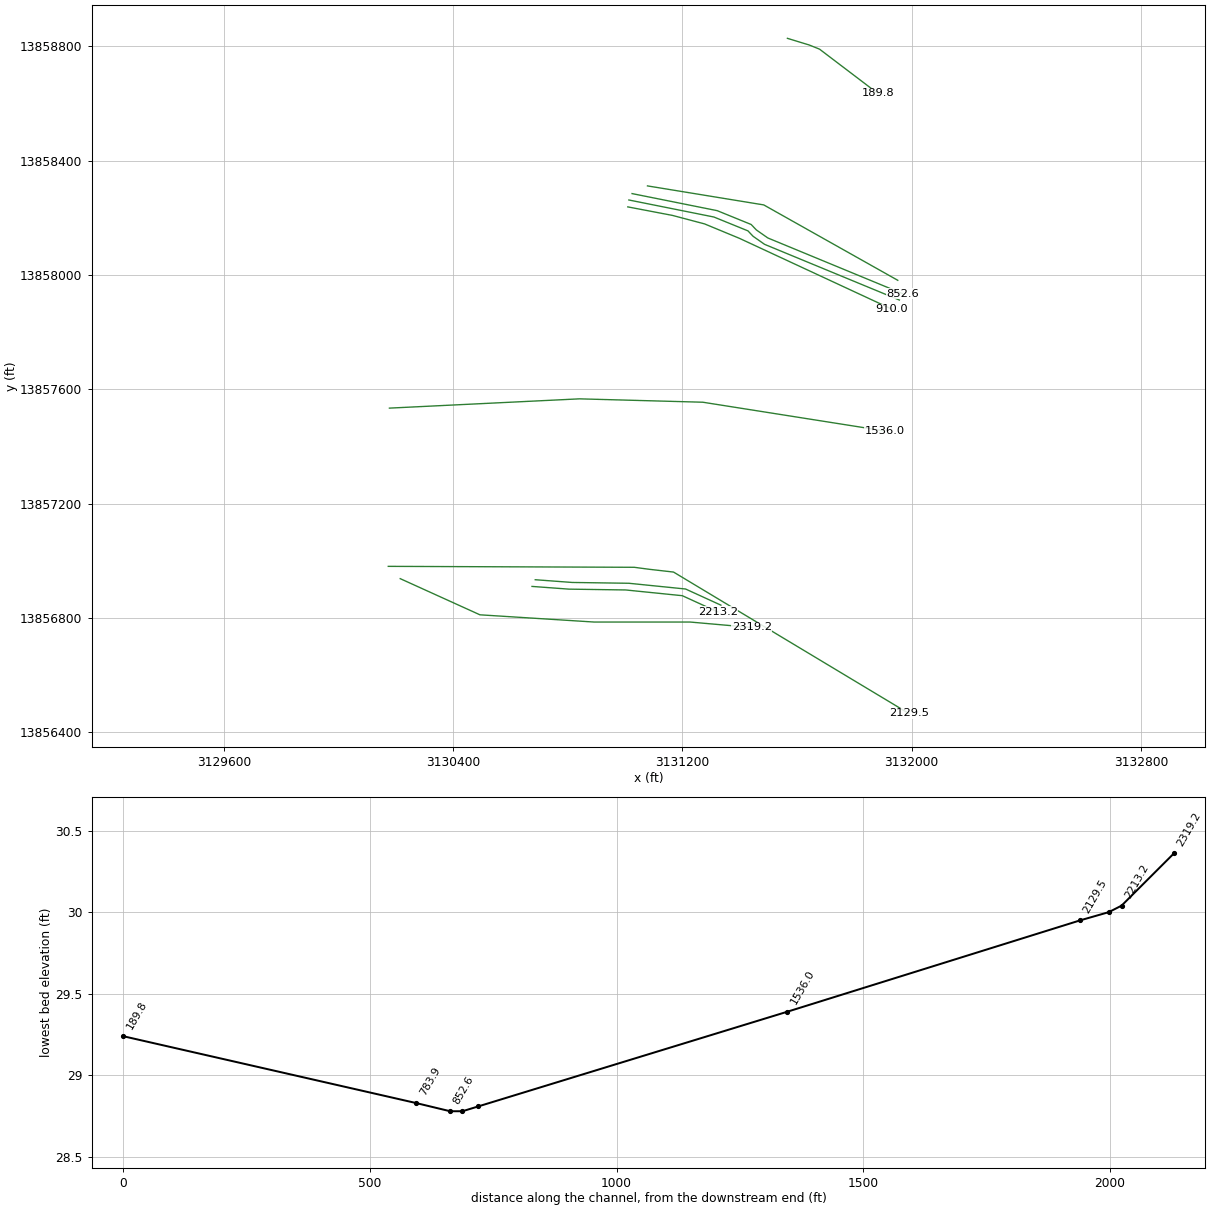
--- H112-00-00.PRJ (project) ---

Proj Title=H112-00-00
Current Plan=p03
Default Exp/Contr=.3,.1
English Units
Geom File=g01
Flow File=f01
Flow File=f03
Plan File=p01
Plan File=p03
Y Axis Title=Elevation
X Axis Title(PF)=Main Channel Distance
X Axis Title(XS)=Station
BEGIN DESCRIPTION:
Hunting Bayou Watershed
Tributary 13.85 to Hunting Bayou
HCFCD Unit H112-00-00
Flood Hazard Model
10, 2, 1, 0.2% Event
Filename H112-00-00.prj
Prepared by:  Watershed Concepts  Date: 06/04/02
Reviewed by:                      Date:
STATUS FINAL
END DESCRIPTION:
DSS Export Rating Curves= 0
DSS Export Rating Curve Sorted= 0
DSS Export Volume Flow Curves= 0
DXF OffsetX= 0
DXF OffsetY= 0
DXF ScaleX= 1
DXF ScaleY= 10

--- H112-00-00.p03 (plan) ---

Plan Title=Floodway
Version=Version 3.0.1  Mar 2001
Short Identifier=Floodway0607
Geom File=g01
Flow File=f03
Subcritical Flow
K Sum by GR= 0
Std Step Tol= 0.01
Critical Tol= 0.01
Num of Std Step Trials= 20
Max Error Tol= 0.3
Flow Tol Ratio= 0.001
Split Flow NTrial= 30
Split Flow Tol= 0.02
Split Flow Ratio= 0.02
Log Output Level= 0
Friction Slope Method= 1
Unsteady Friction Slope Method= 2
Parabolic Critical Depth
Global Vel Dist= 0 , 0 , 0
Global Log Level= 0
CheckData=True
Encroach Param=-1 ,0,0, 2
Encroach River=H112-00-00
Encroach Reach=Reach - 1
Encroach Node=2319.2
       1  4976.5  5024.3
Encroach Node=2213.2
       1  4976.5  5024.3
Encroach Node=2200.2
       1  4976.5  5024.3
Encroach Node=2187.2
       1  4976.5  5024.3
Encroach Node=2129.5
       1  4976.5  5024.3
Encroach Node=1536.0
       1  4971.6  5030.9
Encroach Node=910.0
       1  4971.6  5030.9
Encroach Node=877.6
       1  4971.6  5030.9
Encroach Node=865.1
       1  4971.6  5030.9
Encroach Node=852.6
       1  4971.6  5030.9
Encroach Node=783.9
       1  4971.6  5030.9
Encroach Node=189.8
       1 4976.04 5026.54
Encroach Reach=H112-00-00_0002
Encroach Node=2319.2
       1  4976.5  5024.3
Encroach Node=2213.2
       1  4976.5  5024.3
Encroach Node=2200.2
       1  4976.5  5024.3
Encroach Node=2187.2
       1  4976.5  5024.3
Encroach Node=2129.5
       1  4976.5  5024.3
Encroach Node=1536.0
       1  4971.6  5030.9
Encroach Node=910.0
       1  4971.6  5030.9
Encroach Node=877.6
       1  4971.6  5030.9
Encroach Node=865.1
       1  4971.6  5030.9
Encroach Node=852.6
       1  4971.6  5030.9
Encroach Node=783.9
       1  4971.6  5030.9
Encroach Node=189.8
       1 4976.04 5026.54
Computation Interval=1HOUR
Output Interval=1HOUR
Run HTab= 0
Run UNet= 0
Run PostProcess= 0
UNET Theta= 1
UNET ZTol= 0.02
UNET ZSATol= 0.1
UNET MxIter= 20
UNET MaxInSteps= 20
UNET DtIC= 0
UNET DtMin= 0
UNET MaxCRTS= 20
UNET WFStab= 2
UNET SFStab= 1
UNET WFX= 1
UNET SFX= 1
UNET Convert EG Bridges=-1
UNET Use Existing IB Tables=-1
Instantaneous Interval=1HOUR
Write IC File= 0
Write Velocity= 0
Write Detailed= 0

--- H112-00-00.p01 (plan) ---

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Plan Title=FEMA Effective June 2007
Short Identifier=FEMAeff0607
Geom File=g01
Flow File=f01
Encroach Param=-1 ,0,0, 0

--- H112-00-00.f03 (steady flow) ---

Flow Title= Floodway
Number of Profiles= 2
Profile Names=1PCT_100yr, 1PCTFloodway_100yrFW
River Rch & RM=H112-00-00,H112-00-00_0002,2319.2
     507     507
River Rch & RM=H112-00-00,H112-00-00_0002,189.8
     534     534
Boundary for River Rch & Prof#=H112-00-00,H112-00-00_0002, 1
Up Type= 0
Dn Type= 3
Dn Slope= 0.00050
Boundary for River Rch & Prof#=H112-00-00,H112-00-00_0002, 2
Up Type= 0
Dn Type= 1
Dn Known WS=40.22

--- H112-00-00.f01 (steady flow) ---

Flow Title= FEMA Effective June 2007
Number of Profiles= 4
Profile Names=10PCT_10yr, 2PCT_50yr, 1PCT_100yr, 0.2PCT_500yr
River Rch & RM=H112-00-00,H112-00-00_0002,2319.2
     273     424     507     763
River Rch & RM=H112-00-00,H112-00-00_0002,189.8
     288     447     534     804
Boundary for River Rch & Prof#=H112-00-00,H112-00-00_0002, 1
Up Type= 0
Dn Type= 3
Dn Slope= 0.00050
Boundary for River Rch & Prof#=H112-00-00,H112-00-00_0002, 2
Up Type= 0
Dn Type= 3
Dn Slope= 0.00050
Boundary for River Rch & Prof#=H112-00-00,H112-00-00_0002, 3
Up Type= 0
Dn Type= 3
Dn Slope= 0.00050
Boundary for River Rch & Prof#=H112-00-00,H112-00-00_0002, 4
Up Type= 0
Dn Type= 3
Dn Slope= 0.00050

--- H112-00-00.g01 (geometry) ---

Geom Title=H112-00-00 June 2007

River Reach=H112-00-00,H112-00-00_0002
Reach XY= 20
      3131067.96     13856786.20      3131070.01     13856791.07
      3131079.89     13856887.95       3131113.5     13856957.15
      3131124.75        13857066      3131131.75        13857182
      3131137.23     13857267.55      3131153.91     13857381.78
      3131166.25        13857518       3131178.5        13857651
       3131197.4     13857771.32       3131213.5        13857862
      3131303.75        13858045      3131376.75        13858169
       3131415.5        13858246      3131468.25        13858384
      3131514.25        13858500      3131574.49     13858637.91
      3131629.52     13858740.48      3131663.58     13858797.48
      3131710.12     13858863.96      3131756.75        13858900

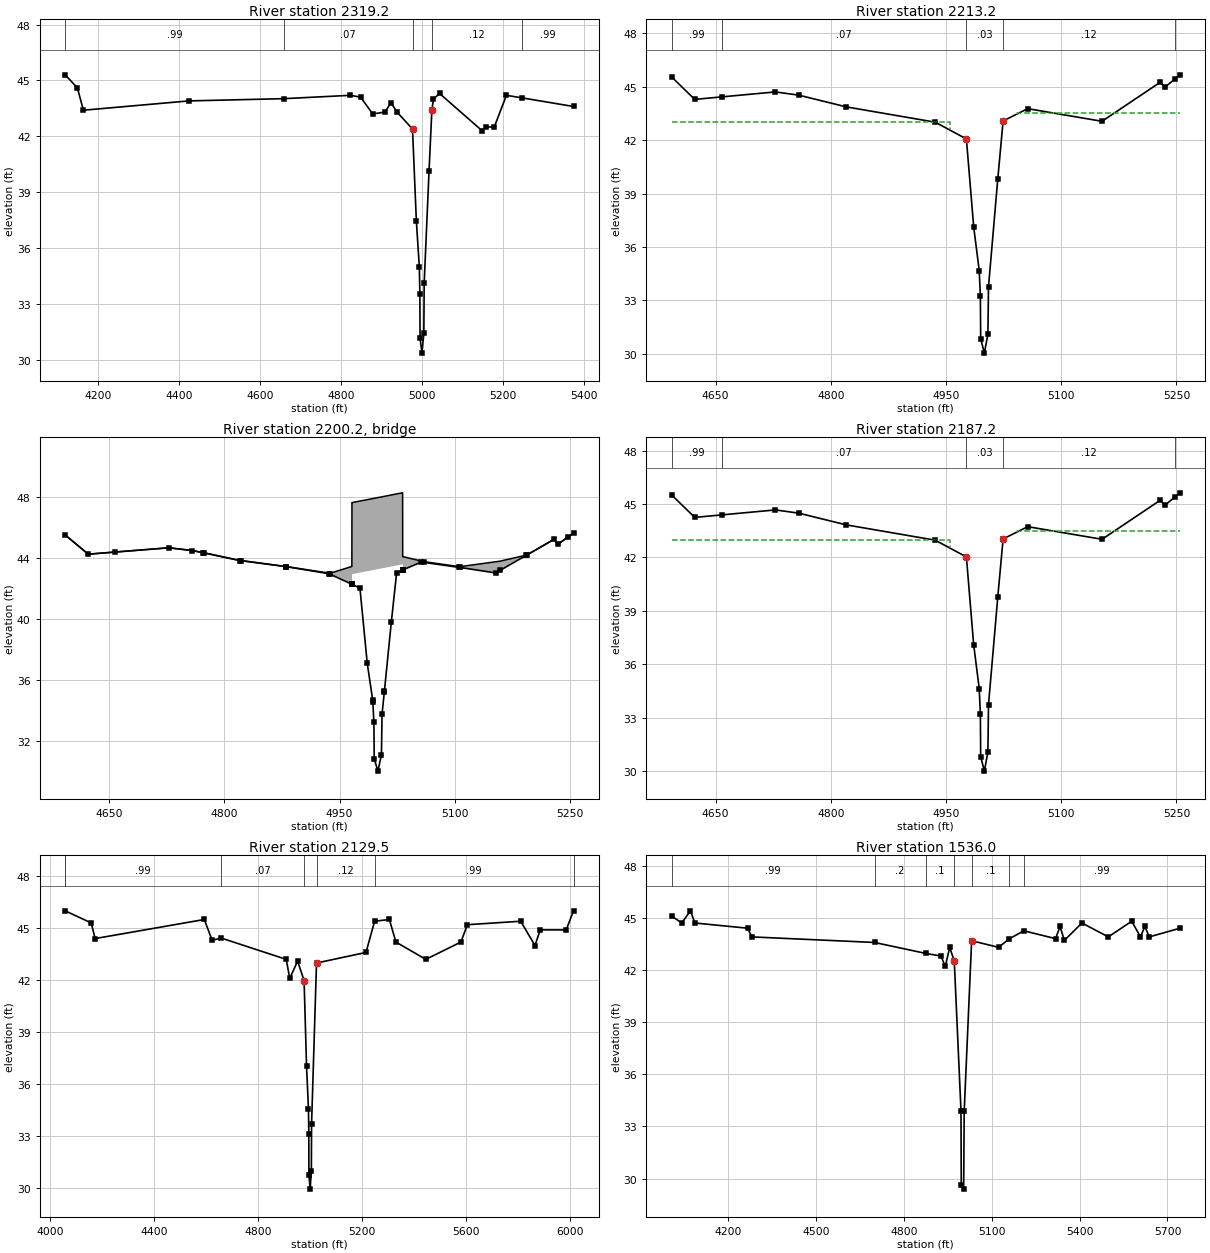
Type RM Length L Ch R = 1 ,2319.2,106.3,106,104.8
XS GIS Cut Line= 5
      3130214.68     13856937.93      3130492.91     13856811.46
      3130891.30     13856786.17      3131226.44     13856786.17
      3131441.45     13856767.20
BEGIN DESCRIPTION:
Cross Section 2319.2 - Interpolated
END DESCRIPTION:
#Sta/Elev= 29
  4118.5    45.3  4148.5    44.6  4163.5    43.4  4424.1    43.9  4657.8   44.02
  4823.3    44.2  4848.3    44.1  4878.3    43.2  4908.3    43.3  4923.3    43.8
  4938.3    43.3  4976.5   42.39    4986   37.45  4993.3      35  4994.7   33.56
  4995.1   31.18  4999.9   30.36  5004.5   31.43  5005.3    34.1  5017.4   40.16
  5024.3    43.4  5028.3      44  5043.3    44.3  5148.3    42.3  5158.5    42.5
  5178.5    42.5  5208.5    44.2  5247.8   44.06  5374.3    43.6
#Mann= 5 , 1 , 0
 4118.50    0.99       0  4657.8    0.07       0  4976.5    0.03       0
  5024.3    0.12       0  5247.8    0.99       0
Bank Sta=4976.50,5024.30
Exp/Cntr=0.5,0.3

Type RM Length L Ch R = 1 ,2213.2,26,26,26
XS GIS Cut Line= 5
      3130674.63     13856910.78      3130803.80     13856901.26
      3131001.59     13856898.40      3131199.38     13856878.33
      3131322.73     13856821.85
BEGIN DESCRIPTION:
Upstream Section of Bridge/Culvert/Weir
END DESCRIPTION:
#Sta/Elev= 23
  4592.8   45.55  4622.8   44.29  4657.8   44.43  4727.8   44.71  4758.1   44.53
  4820.1   43.87  4935.9   43.01  4976.5   42.07    4986   37.13  4993.2   34.68
  4994.7   33.24  4995.1   30.86  4999.9   30.04  5004.5   31.11  5005.3   33.78
  5017.4   39.84  5024.3   43.08  5056.3   43.77  5153.1   43.06  5229.1   45.26
  5234.6   44.96  5247.8   45.43  5254.6   45.67
#Mann= 5 , 1 , 0
 4592.80    0.99       0  4657.8    0.07       0  4976.5    0.03       0
  5024.3    0.12       0  5247.8    0.99       0
#XS Ineff= 2 , 0
       0    4955      43    5043       0    43.5
Bank Sta=4976.50,5024.30
Exp/Cntr=0.5,0.3

Type RM Length L Ch R = 3 ,2200.2,,,
BEGIN DESCRIPTION:
CROSSING D/S OF CALVACADE
Structure ID: H12-3
END DESCRIPTION:
Bridge Culvert--1,0,-1,-1, 0
Deck Dist Width WeirC Skew NumUp NumDn MinLoCord MaxHiCord MaxSubmerge Is_Ogee
10,6,2.6,,50,50,,,0.95,0,1,1,,
  4592.8  4622.8  4657.8  4727.8  4758.1  4771.7  4773.8  4820.1  4822.2  4880.3
  4880.4  4935.9  4937.8  4965.8 4965.91 4965.99  4966.1  4966.2 4966.31  4976.5
    4986  4993.2  4993.3  4994.7  4995.1  4999.9  5004.5  5005.3  5008.3  5008.4
  5017.4  5024.3 5031.99  5032.1 5032.21 5032.29  5032.4  5032.5  5056.3  5059.8
  5106.1  5106.4  5153.1  5158.8  5193.3  5194.1  5229.1  5234.6  5247.8  5254.6
   45.52   44.26    44.4   44.68    44.5   44.37   44.35   43.85   43.84   43.45
   43.45   43.02   43.01   43.45   43.45   43.45   47.65   47.65   47.65   47.75
   47.84   47.91   47.91   47.93   47.93   47.98   48.02   48.03   48.06   48.06
   48.15   48.22   48.29   48.29   44.09   44.09    44.1    44.1   43.81   43.77
   43.44   43.44   43.76    43.8    44.2   44.22   45.23   44.93    45.4   45.64
   45.52   44.26    44.4   44.68    44.5   44.36   44.34   43.84   43.83   43.44
   43.44   42.98   42.94   42.29   42.29   42.28   42.28   42.95   42.95   43.05
   43.14   43.21   43.21   43.23   43.23   43.28   43.32   43.33   43.36   43.36
   43.45   43.52   43.59   43.59   43.59   43.59   43.22   43.23   43.74   43.72
   43.39   43.39   43.03   43.19   44.19   44.21   45.23   44.93    45.4   45.64
  4592.8  4622.8  4657.8  4727.8  4758.1  4771.7  4773.8  4820.1  4822.2  4880.3
  4880.4  4935.9  4937.8  4965.8 4965.91 4965.99  4966.1  4966.2 4966.31  4976.5
    4986  4993.2  4993.3  4994.7  4995.1  4999.9  5004.5  5005.3  5008.3  5008.4
  5017.4  5024.3 5031.99  5032.1 5032.21 5032.29  5032.4  5032.5  5056.3  5059.8
  5106.1  5106.4  5153.1  5158.8  5193.3  5194.1  5229.1  5234.6  5247.8  5254.6
   45.52   44.26    44.4   44.68    44.5   44.37   44.35   43.85   43.84   43.45
   43.45   43.02   43.01   43.45   43.45   43.45   47.65   47.65   47.65   47.75
   47.84   47.91   47.91   47.93   47.93   47.98   48.02   48.03   48.06   48.06
   48.15   48.22   48.29   48.29   44.09   44.09    44.1    44.1   43.81   43.77
   43.44   43.44   43.76    43.8    44.2   44.22   45.23   44.93    45.4   45.64
   45.52   44.26    44.4   44.68    44.5   44.36   44.34   43.84   43.83   43.44
   43.44   42.98   42.94   42.29   42.29   42.28   42.28   42.95   42.95   43.05
   43.14   43.21   43.21   43.23   43.23   43.28   43.32   43.33   43.36   43.36
   43.45   43.52   43.59   43.59   43.59   43.59   43.22   43.23   43.74   43.72
   43.39   43.39   43.03   43.19   44.19   44.21   45.23   44.93    45.4   45.64
Abutment Skew #Up #Dn=, 2 , 2
 4966.00 4993.30
   42.95   34.55
 4966.00 4993.30
   42.95   34.55
Abutment Skew #Up #Dn=, 2 , 2
 5008.40 5032.49
   35.28   43.59
 5008.40 5032.49
   35.28   43.59
BR Coef= 1 , 1 , 0 ,1.25, 0 ,,,0.8,0,2,0,
Wspro=,,,, 1 ,,,, 0 ,,,, 0 ,,,,-1 ,-1 ,-1 , 0 , 0 , 0 , 0 , 0
BC Design=,, 0 ,, 0 ,,,,,,
BR U #Sta/Elev= 50
  4592.8   45.52  4622.8   44.26  4657.8    44.4  4727.8   44.68  4758.1    44.5
  4771.7   44.36  4773.8   44.34  4820.1   43.84  4822.2   43.83  4880.3   43.44
  4880.4   43.44  4935.9   42.98  4937.8   42.94  4965.8   42.29 4965.91   42.29
 4965.99   42.28  4966.1   42.28  4966.2   42.28 4966.31   42.28  4976.5   42.04
    4986    37.1  4993.2   34.65  4993.3   34.55  4994.7   33.21  4995.1   30.83
  4999.9   30.01  5004.5   31.08  5005.3   33.75  5008.3   35.23  5008.4   35.28
  5017.4   39.81  5024.3   43.05 5031.99   43.22  5032.1   43.22 5032.21   43.22
 5032.29   43.22  5032.4   43.22  5032.5   43.23  5056.3   43.74  5059.8   43.72
  5106.1   43.39  5106.4   43.39  5153.1   43.03  5158.8   43.19  5193.3   44.19
  5194.1   44.21  5229.1   45.23  5234.6   44.93  5247.8    45.4  5254.6   45.64
BR U #Mann= 5
 4592.80    0.99  4657.8    0.07  4976.5    0.03  5024.3    0.12  5247.8    0.99
BR U Banks=4976.50,5024.30
BR D #Sta/Elev= 50
  4592.8   45.52  4622.8   44.26  4657.8    44.4  4727.8   44.68  4758.1    44.5
  4771.7   44.36  4773.8   44.34  4820.1   43.84  4822.2   43.83  4880.3   43.44
  4880.4   43.44  4935.9   42.98  4937.8   42.94  4965.8   42.29 4965.91   42.29
 4965.99   42.28  4966.1   42.28  4966.2   42.28 4966.31   42.28  4976.5   42.04
    4986    37.1  4993.2   34.65  4993.3   34.55  4994.7   33.21  4995.1   30.83
  4999.9   30.01  5004.5   31.08  5005.3   33.75  5008.3   35.23  5008.4   35.28
  5017.4   39.81  5024.3   43.05 5031.99   43.22  5032.1   43.22 5032.21   43.22
 5032.29   43.22  5032.4   43.22  5032.5   43.23  5056.3   43.74  5059.8   43.72
  5106.1   43.39  5106.4   43.39  5153.1   43.03  5158.8   43.19  5193.3   44.19
  5194.1   44.21  5229.1   45.23  5234.6   44.93  5247.8    45.4  5254.6   45.64
BR D #Mann= 5
 4592.80    0.99  4657.8    0.07  4976.5    0.03  5024.3    0.12  5247.8    0.99
BR D Banks=4976.50,5024.30

Type RM Length L Ch R = 1 ,2187.2,57.7,57.7,57.7
XS GIS Cut Line= 5
      3130685.99     13856934.17      3130815.16     13856924.64
      3131012.95     13856921.78      3131210.74     13856901.71
      3131334.08     13856845.24
BEGIN DESCRIPTION:
Downstream Section of Bridge/Culvert/Weir
END DESCRIPTION:
#Sta/Elev= 23
  4592.8   45.51  4622.8   44.25  4657.8   44.39  4727.8   44.67  4758.1   44.49
  4820.1   43.83  4935.9   42.97  4976.5   42.03    4986   37.09  4993.2   34.64
  4994.7    33.2  4995.1   30.82  4999.9      30  5004.5   31.07  5005.3   33.74
  5017.4    39.8  5024.3   43.04  5056.3   43.73  5153.1   43.02  5229.1   45.22
  5234.6   44.92  5247.8   45.39  5254.6   45.63
#Mann= 5 , 1 , 0
 4592.80    0.99       0  4657.8    0.07       0  4976.5    0.03       0
  5024.3    0.12       0  5247.8    0.99       0
#XS Ineff= 2 , 0
       0    4955      43    5043       0    43.5
Bank Sta=4976.50,5024.30
Exp/Cntr=0.5,0.3

Type RM Length L Ch R = 1 ,2129.5,594.7,593.5,589.9
XS GIS Cut Line= 6
      3130172.98     13856980.96      3131031.67     13856977.67
      3131083.86     13856970.71      3131126.31     13856965.84
      3131168.75     13856960.97      3131989.56     13856466.67
BEGIN DESCRIPTION:
Cross Section 2129.5 - Interpolated
END DESCRIPTION:
#Sta/Elev= 30
  4057.8      46  4157.8    45.3  4172.8    44.4  4592.8    45.5  4622.8    44.3
  4657.8   44.43  4907.8    43.2  4921.5    42.1  4951.5    43.1  4976.5   41.98
    4986   37.04  4993.3   34.59  4994.7   33.15  4995.1   30.77  4999.9   29.95
  5004.5   31.02  5005.3   33.69  5024.3   42.99  5214.6    43.6  5247.8    45.4
  5304.6    45.5  5329.6    44.2  5444.6    43.2  5579.6    44.2  5604.6    45.2
  5809.6    45.4  5864.6      44  5884.6    44.9  5984.6    44.9  6012.8      46
#Mann= 7 , 1 , 0
 4057.80    0.99       0  4057.8    0.99       0  4657.8    0.07       0
  4976.5    0.03       0  5024.3    0.12       0  5247.8    0.99       0
  6012.8     0.2       0
Bank Sta=4976.50,5024.30
Exp/Cntr=0.3,0.1

Type RM Length L Ch R = 1 ,1536.0,657.3,626,608.2
XS GIS Cut Line= 4
      3130176.94     13857534.47      3130840.38     13857566.91
      3131270.87     13857555.11      3131904.82     13857454.86
BEGIN DESCRIPTION:
Cross Section 1536.0 - Interpolated
END DESCRIPTION:
#Sta/Elev= 30
  4006.1    45.1  4040.3    44.7  4070.3    45.4  4085.3    44.7  4265.3    44.4
  4280.3    43.9  4699.2   43.58  4874.2   42.95    4926    42.8    4941    42.2
    4956    43.3  4971.6   42.51  4994.5   33.91  4995.5   29.62  5003.7   29.39
  5005.5   33.86  5030.9   43.68  5122.8    43.3  5159.7   43.79  5209.2   44.25
  5317.8    43.8  5332.8    44.5  5347.8    43.7  5407.8    44.7  5497.8    43.9
  5577.8    44.8  5607.8    43.9  5622.8    44.5  5637.8    43.9  5742.8    44.4
#Mann= 7 , 1 , 0
 4006.10    0.99       0  4699.2     0.2       0  4874.2     0.1       0
  4971.6    0.03       0  5030.9     0.1       0  5159.7     0.2       0
  5209.2    0.99       0
Bank Sta=4971.60,5030.90
Exp/Cntr=0.3,0.1

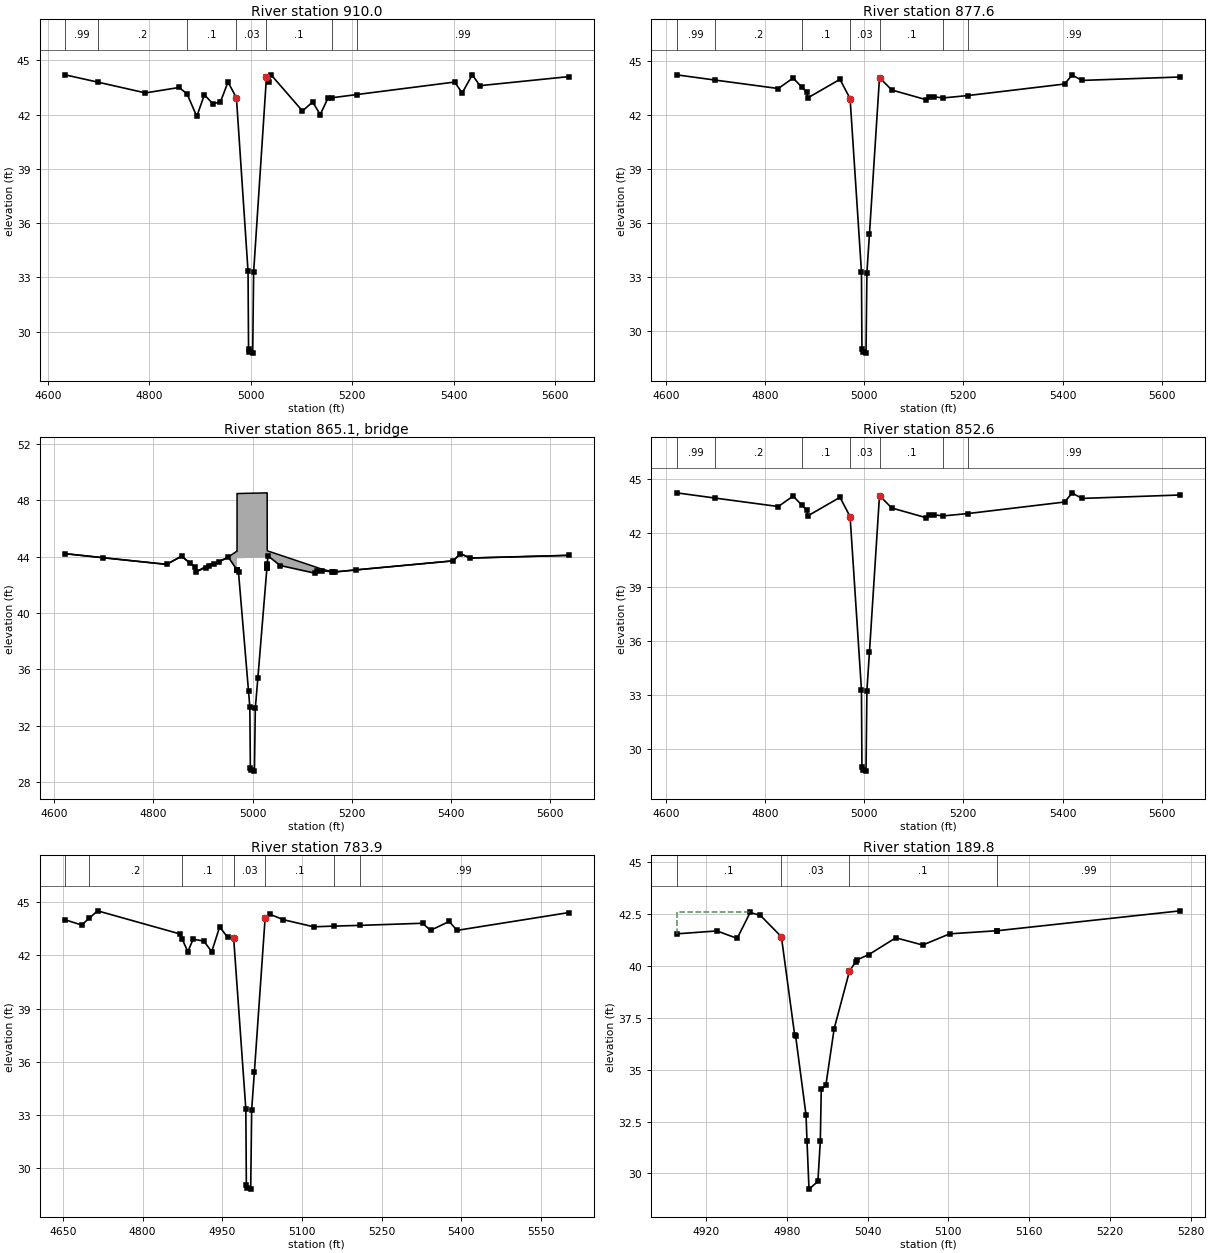
Type RM Length L Ch R = 1 ,910.0,34.2,32.4,31.8
XS GIS Cut Line= 5
      3131008.99     13858238.42      3131164.92     13858208.61
      3131277.29     13858178.80      3131398.83     13858128.35
      3131930.85     13857880.68
BEGIN DESCRIPTION:
Cross Section 910.0 - Interpolated
END DESCRIPTION:
#Sta/Elev= 30
  4633.4    44.2  4699.2   43.79  4792.2    43.2  4858.4    43.5  4874.2   43.15
  4893.4    41.9  4908.4    43.1    4925    42.6    4940    42.7    4955    43.8
  4971.6   42.93  4994.5   33.33  4995.5   29.04    4997   28.88  5003.7   28.81
  5005.5   33.28  5030.9    44.1    5035    43.8    5040    44.2  5101.9    42.2
  5121.9    42.7  5136.9      42  5151.9    42.9  5159.7   42.93  5209.2   43.11
  5401.9    43.8  5416.9    43.2  5436.9    44.2  5451.9    43.6  5626.9    44.1
#Mann= 7 , 1 , 0
 4633.40    0.99       0  4699.2     0.2       0  4874.2     0.1       0
  4971.6    0.03       0  5030.9     0.1       0  5159.7     0.2       0
  5209.2    0.99       0
Bank Sta=4971.60,5030.90
Exp/Cntr=0.5,0.3

Type RM Length L Ch R = 1 ,877.6,25,25,25
XS GIS Cut Line= 6
      3131012.71     13858262.56      3131309.82     13858202.91
      3131428.50     13858154.50      3131446.44     13858135.56
      3131486.59     13858107.38      3131957.10     13857912.57
BEGIN DESCRIPTION:
Upstream Section of Bridge/Culvert/Weir
END DESCRIPTION:
#Sta/Elev= 26
  4621.7   44.22  4699.2   43.93  4826.7   43.46  4856.7   44.04  4874.2   43.54
  4884.7   43.24  4886.3   42.94  4951.2   43.97  4971.6    42.9  4994.5    33.3
  4995.5   29.01    4997   28.85  5003.7   28.78  5005.5   33.25  5010.6   35.37
  5030.9   44.07  5055.5   43.38  5124.9   42.84  5130.5   42.97  5139.8      43
  5159.7   42.94  5209.2   43.07  5404.2   43.71  5419.2   44.21  5439.2   43.91
  5637.3    44.1
#Mann= 7 , 1 , 0
 4621.70    0.99       0  4699.2     0.2       0  4874.2     0.1       0
  4971.6    0.03       0  5030.9     0.1       0  5159.7     0.2       0
  5209.2    0.99       0
#XS Ineff= 2 , 0
       0  4968.5   43.05    5029       0   43.25
Bank Sta=4971.60,5030.90
Exp/Cntr=0.5,0.3

Type RM Length L Ch R = 3 ,865.1,,,
BEGIN DESCRIPTION:
GEORGE STREET
Structure ID: H12-2
END DESCRIPTION:
Bridge Culvert--1,0,-1,-1, 0
Deck Dist Width WeirC Skew NumUp NumDn MinLoCord MaxHiCord MaxSubmerge Is_Ogee
10,5,2.6,,47,47,,,0.95,0,1,1,,
  4621.7  4699.2  4826.7  4856.7  4874.2  4884.7  4886.3  4905.1    4913  4922.5
  4933.2  4951.2  4968.2 4968.31  4968.4 4968.49  4968.6  4968.7 4968.81  4971.6
  4991.8  4994.5  4995.5    4997  5003.7  5005.5  5010.6  5028.8 5028.89    5029
  5029.2 5029.29  5029.4 5029.51  5030.9  5055.5  5124.9  5130.5  5139.8  5159.7
  5162.3  5165.3  5209.2  5404.2  5419.2  5439.2  5637.3
   44.21   43.92   43.45   44.03   43.53   43.23   42.93   43.29   43.47    43.5
   43.66   43.98   44.38   44.38   44.38   44.38   44.38   48.48   48.48   48.48
    48.5    48.5    48.5    48.5   48.51   48.51   48.51   48.53   48.53   48.53
   48.52   48.52   48.52   44.42    44.4   44.11   43.29   43.22   43.11   42.94
   42.93   42.91   43.06    43.7    44.2    43.9   44.09
   44.21   43.92   43.45   44.03   43.53   43.23   42.93   43.22   43.34   43.49
   43.65   43.96   43.07   43.06   43.06   43.05   43.88   43.88   43.88   43.88
    43.9    43.9    43.9    43.9   43.91   43.91   43.91   43.93   43.93   43.25
   43.33   43.37   43.42   43.46   44.06   43.37   42.83   42.96   42.99   42.93
   42.92   42.91   43.06    43.7    44.2    43.9   44.09
  4621.7  4699.2  4826.7  4856.7  4874.2  4884.7  4886.3  4905.1    4913  4922.5
  4933.2  4951.2  4968.2 4968.31  4968.4 4968.49  4968.6  4968.7 4968.81  4971.6
  4991.8  4994.5  4995.5    4997  5003.7  5005.5  5010.6  5028.8 5028.89    5029
  5029.2 5029.29  5029.4 5029.51  5030.9  5055.5  5124.9  5130.5  5139.8  5159.7
  5162.3  5165.3  5209.2  5404.2  5419.2  5439.2  5637.3
   44.21   43.92   43.45   44.03   43.53   43.23   42.93   43.29   43.47    43.5
   43.66   43.98   44.38   44.38   44.38   44.38   44.38   48.48   48.48   48.48
    48.5    48.5    48.5    48.5   48.51   48.51   48.51   48.53   48.53   48.53
   48.52   48.52   48.52   44.42    44.4   44.11   43.29   43.22   43.11   42.94
   42.93   42.91   43.06    43.7    44.2    43.9   44.09
   44.21   43.92   43.45   44.03   43.53   43.23   42.93   43.22   43.34   43.49
   43.65   43.96   43.07   43.06   43.06   43.05   43.88   43.88   43.88   43.88
    43.9    43.9    43.9    43.9   43.91   43.91   43.91   43.93   43.93   43.25
   43.33   43.37   43.42   43.46   44.06   43.37   42.83   42.96   42.99   42.93
   42.92   42.91   43.06    43.7    44.2    43.9   44.09
BR Coef= 1 , 1 , 0 ,1.25, 0 ,,,0.8,0,2,0,
Wspro=,,,, 1 ,,,, 0 ,,,, 0 ,,,,-1 ,-1 ,-1 , 0 , 0 , 0 , 0 , 0
BC Design=,, 0 ,, 0 ,,,,,,
BR U #Sta/Elev= 47
  4621.7   44.21  4699.2   43.92  4826.7   43.45  4856.7   44.03  4874.2   43.53
  4884.7   43.23  4886.3   42.93  4905.1   43.22    4913   43.34  4922.5   43.49
  4933.2   43.65  4951.2   43.96  4968.2   43.07 4968.31   43.06  4968.4   43.06
 4968.49   43.05  4968.6   43.05  4968.7   43.04 4968.81   43.04  4971.6   42.89
  4991.8   34.45  4994.5   33.29  4995.5      29    4997   28.84  5003.7   28.77
  5005.5   33.24  5010.6   35.36  5028.8   43.16 5028.89    43.2    5029   43.25
  5029.2   43.33 5029.29   43.37  5029.4   43.42 5029.51   43.46  5030.9   44.06
  5055.5   43.37  5124.9   42.83  5130.5   42.96  5139.8   42.99  5159.7   42.93
  5162.3   42.92  5165.3   42.91  5209.2   43.06  5404.2    43.7  5419.2    44.2
  5439.2    43.9  5637.3   44.09
BR U #Mann= 7
 4621.70    0.99  4699.2     0.2  4874.2     0.1  4971.6    0.03  5030.9     0.1
  5159.7     0.2  5209.2    0.99
BR U Banks=4971.60,5030.90
BR D #Sta/Elev= 47
  4621.7   44.21  4699.2   43.92  4826.7   43.45  4856.7   44.03  4874.2   43.53
  4884.7   43.23  4886.3   42.93  4905.1   43.22    4913   43.34  4922.5   43.49
  4933.2   43.65  4951.2   43.96  4968.2   43.07 4968.31   43.06  4968.4   43.06
 4968.49   43.05  4968.6   43.05  4968.7   43.04 4968.81   43.04  4971.6   42.89
  4991.8   34.45  4994.5   33.29  4995.5      29    4997   28.84  5003.7   28.77
  5005.5   33.24  5010.6   35.36  5028.8   43.16 5028.89    43.2    5029   43.25
  5029.2   43.33 5029.29   43.37  5029.4   43.42 5029.51   43.46  5030.9   44.06
  5055.5   43.37  5124.9   42.83  5130.5   42.96  5139.8   42.99  5159.7   42.93
  5162.3   42.92  5165.3   42.91  5209.2   43.06  5404.2    43.7  5419.2    44.2
  5439.2    43.9  5637.3   44.09
BR D #Mann= 7
 4621.70    0.99  4699.2     0.2  4874.2     0.1  4971.6    0.03  5030.9     0.1
  5159.7     0.2  5209.2    0.99
BR D Banks=4971.60,5030.90

Type RM Length L Ch R = 1 ,852.6,68.7,68.7,68.7
XS GIS Cut Line= 6
      3131023.95     13858284.89      3131321.06     13858225.25
      3131439.74     13858176.84      3131457.68     13858157.90
      3131497.83     13858129.72      3131968.34     13857934.90
BEGIN DESCRIPTION:
Downstream Section of Bridge/Culvert/Weir
END DESCRIPTION:
#Sta/Elev= 26
  4621.7   44.22  4699.2   43.93  4826.7   43.46  4856.7   44.04  4874.2   43.54
  4884.7   43.24  4886.3   42.94  4951.2   43.97  4971.6    42.9  4994.5    33.3
  4995.5   29.01    4997   28.85  5003.7   28.78  5005.5   33.25  5010.6   35.37
  5030.9   44.07  5055.5   43.38  5124.9   42.84  5130.5   42.97  5139.8      43
  5159.7   42.94  5209.2   43.07  5404.2   43.71  5419.2   44.21  5439.2   43.91
  5637.3    44.1
#Mann= 7 , 1 , 0
 4621.70    0.99       0  4699.2     0.2       0  4874.2     0.1       0
  4971.6    0.03       0  5030.9     0.1       0  5159.7     0.2       0
  5209.2    0.99       0
#XS Ineff= 2 , 0
       0  4968.5   43.05    5029       0   43.25
Bank Sta=4971.60,5030.90
Exp/Cntr=0.5,0.3

Type RM Length L Ch R = 1 ,783.9,594.2,594.1,585.4
XS GIS Cut Line= 3
      3131077.78     13858311.80      3131483.68     13858245.30
      3131951.49     13857981.58
BEGIN DESCRIPTION:
Cross Section 783.9 - Interpolated
END DESCRIPTION:
#Sta/Elev= 30
    4654      44  4685.3    43.7  4699.2   44.07  4715.3    44.5  4870.3    43.2
  4874.2   42.94  4885.3    42.2  4895.3    42.9  4915.3    42.8  4930.3    42.2
  4945.3    43.6  4960.3      43  4971.6   42.95  4994.5   33.35  4995.5   29.06
    4997    28.9  5003.7   28.83  5005.5    33.3  5010.6   35.42  5030.9   44.12
  5040.3    44.3  5065.3      44  5122.3    43.6  5159.7   43.64  5209.2   43.68
  5327.3    43.8  5342.3    43.4  5377.3    43.9  5392.3    43.4  5602.3    44.4
#Mann= 7 , 1 , 0
 4654.00    0.99       0  4699.2     0.2       0  4874.2     0.1       0
  4971.6    0.03       0  5030.9     0.1       0  5159.7     0.2       0
  5209.2    0.99       0
Bank Sta=4971.60,5030.90
Exp/Cntr=0.3,0.1

Type RM Length L Ch R = 1 ,189.8,0,0,0
XS GIS Cut Line= 4
      3131566.24     13858828.01      3131642.78     13858804.56
      3131678.45     13858790.13      3131881.77     13858635.45
BEGIN DESCRIPTION:
Cross Section 189.8
END DESCRIPTION:
#Sta/Elev= 26
  4898.2   41.55  4928.2   41.69  4943.2   41.33 4952.84   42.58 4960.44   42.44
 4976.04   41.41 4985.94   36.65 4986.64   36.61 4994.34   32.81 4995.04   31.58
 4996.54   29.24 5003.14   29.61 5004.94   31.55 5005.64   34.05 5009.04   34.24
 5015.24   36.98 5026.54   39.74 5031.24   40.21 5032.34    40.3    5041   40.55
    5061   41.36    5081   41.01    5101   41.55    5136    41.7  5136.2    41.7
  5272.2   42.66
#Mann= 4 , 1 , 0
 4898.20     0.1       0 4976.04    0.03       0 5026.54     0.1       0
  5136.2    0.99       0
#XS Ineff= 2 , 0
       0  4952.8   42.58               0
Bank Sta=4976.04,5026.54
Exp/Cntr=0.3,0.1

Chan Stop Cuts=-1